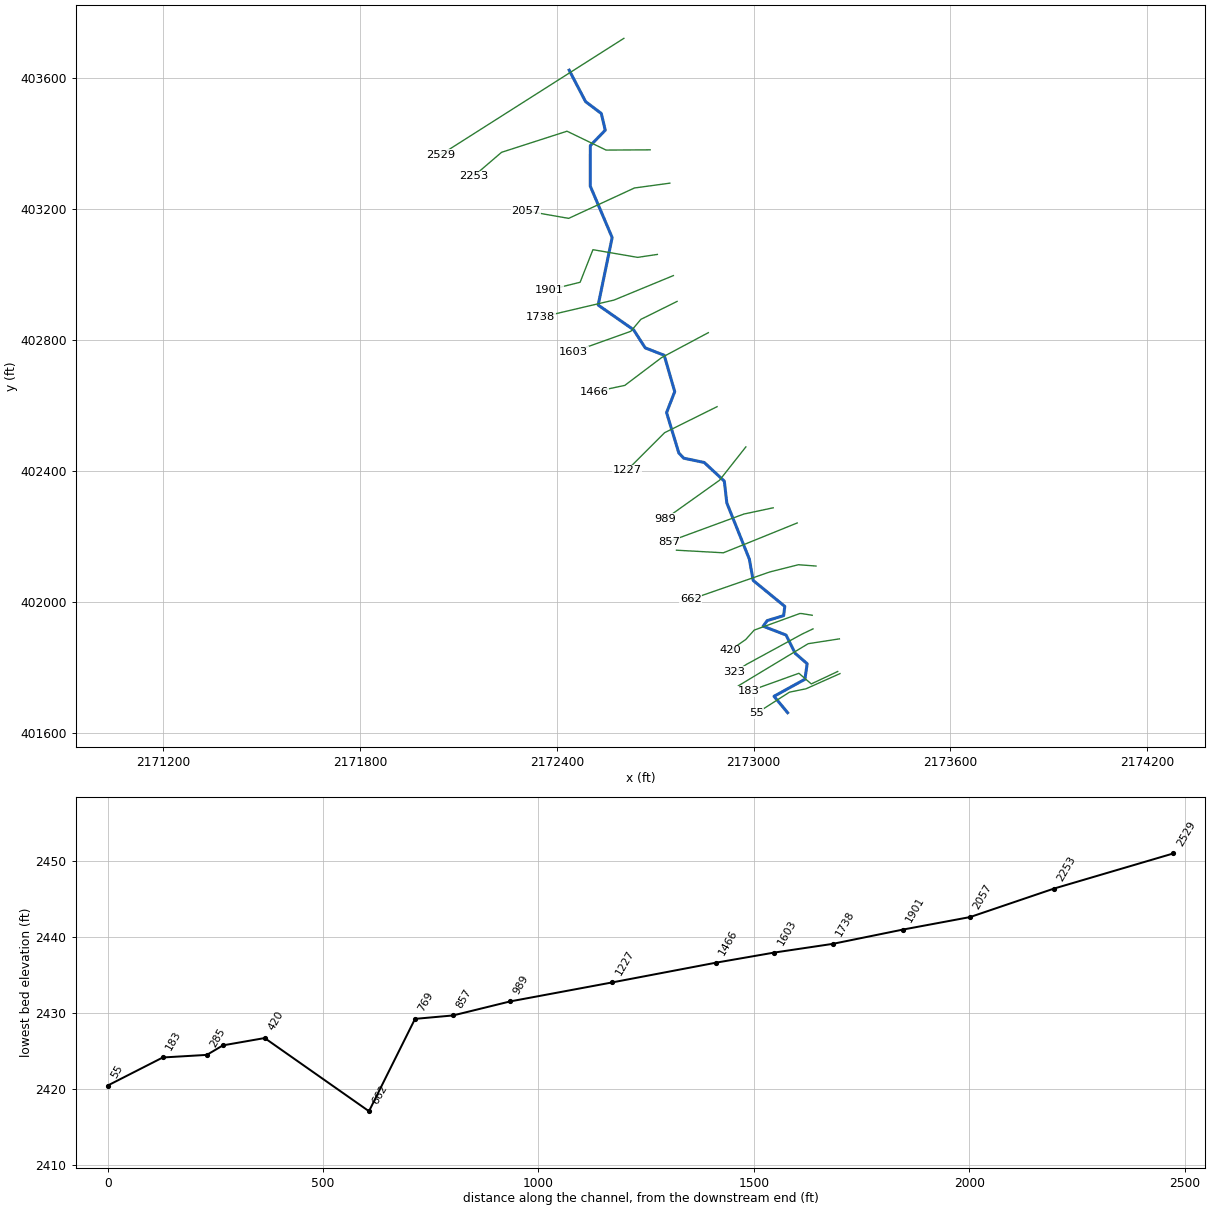
--- RUSHRN.prj (project) ---

Proj Title=RUSHRN
Current Plan=p01
Default Exp/Contr=0,0
English Units
Geom File=g01
Flow File=f01
Plan File=p01
Background Map Layer=Inundation Boundary (01pct Value_0)
BEGIN DESCRIPTION:
----------MODEL BY WOOD PLC 2021----------
Stream Name: Rush Run
Flood Zone: Enhanced Approximate
Pocahontas County, WV
HEC-RAS Version: RAS 6.1
Vertical Datum: NAVD88
Projection: NAD 1983 StatePlane West Virginia S FIPS 4702 (US Feet)
Terrain: 1-meter LIDAR (FEMA Region III 3DEP collected 2016-2018)
Land Use: 2019 NLCD
Hydrologic Method:
WV SIR2010-5033 regression equations
Model Notes:
END DESCRIPTION:
DSS Export Rating Curves= 0
DSS Export Rating Curve Sorted= 0
DSS Export Volume Flow Curves= 0
DXF OffsetX= 0
DXF OffsetY= 0
DXF ScaleX= 0
DXF ScaleY= 0

--- RUSHRN.p01 (plan) ---

Plan Title=Floodplain
Program Version=6.10
Short Identifier=Floodplain
Geom File=g01
Flow File=f01
Subcritical Flow
K Sum by GR= 0
Std Step Tol= 0.01
Critical Tol= 0.01
Num of Std Step Trials= 20
Max Error Tol= 0.3
Flow Tol Ratio= 0.001
Split Flow NTrial= 30
Split Flow Tol= 0.02
Split Flow Ratio= 0.02
Log Output Level= 0
Friction Slope Method= 1
Unsteady Friction Slope Method= 2
Unsteady Bridges Friction Slope Method= 1
Parabolic Critical Depth
Global Vel Dist= 0 , 0 , 0
Global Log Level= 0
CheckData=True
Encroach Param=-1 ,0,0, 0
Mapping Interval=1HOUR
Computation Time Step Use Courant=        0
Computation Time Step Use Time Series=    0
Computation Time Step Count To Double=0
Computation Time Step Max Doubling=0
Computation Time Step Max Halving=0
Computation Time Step Residence Courant=0
Run HTab= 0
Run UNet= 0
Run Sediment= 0
Run PostProcess= 0
Run WQNet= 0
Run RASMapper=-1
UNET Theta= 0
UNET Theta Warmup= 0
UNET ZTol= 0
UNET ZSATol= 0
UNET MxIter= 0
UNET Max Iter WO Improvement= 0
UNET MaxInSteps= 0
UNET DtIC= 0
UNET DtMin= 0
UNET MaxCRTS= 0
UNET WFStab= 0
UNET SFStab= 0
UNET WFX= 1
UNET SFX= 1
UNET Gravity=32.174
UNET 1D Methodology=Finite Difference
UNET DSS MLevel= 1
UNET Pardiso=0
UNET DZMax Abort= 0
UNET Use Existing IB Tables= 0
UNET Froude Reduction=False
UNET Froude Limit= 0
UNET Froude Power= 0
UNET D1 Cores= 0
UNET WindReference=Eulerian
UNET WindDragFormulation=Hsu (1988)
UNET D2 Coriolis=0
UNET D2 Cores= 0
UNET D2 Theta= 1
UNET D2 Theta Warmup= 1
UNET D2 Z Tol= 0.01
UNET D2 Volume Tol= 0.01
UNET D2 Max Iterations= 20
UNET D2 Equation= 0
UNET D2 RampUpFraction=0.1
UNET D2 TimeSlices= 1
UNET D2 Turbulence Formulation=Non-Conservative (original)
UNET D2 Eddy Viscosity=0.3
UNET D2 Transverse Eddy Viscosity=0.1
UNET D2 Smagorinsky Mixing=0
UNET D2 BCVolumeCheck=0
UNET D2 Cores=0
UNET D2 SolverType=PARDISO (Direct)
UNET D2 Minimum Iterations= 2147483647
UNET D2 Maximum Iterations= 2147483647
UNET D2 Restart Number= 10
UNET D2 Relaxation Coeff=1.3
UNET D2 SOR Precondition Iterations= 10
UNET D2 ILUT Maximum Fill= 8
UNET D2 ILUT Tolerance=1E-08
UNET D1D2 MaxIter= 0
UNET D1D2 ZTol=0.01
UNET D1D2 QTol=0.1
UNET D1D2 MinQTol=1
Write IC File= 0
Write IC File at Fixed DateTime=0
Write IC File at Sim End=0
Echo Input=False
Echo Parameters=False
Echo Output=False
Write Detailed= 0
HDF Write Warmup=0
HDF Write Time Slices=0
HDF Flush=0
HDF Compression= 1
HDF Chunk Size= 1
HDF Spatial Parts= 1
HDF Use Max Rows=0
HDF Fixed Rows= 1
Calibration Method= 0
Calibration Iterations= 20
Calibration Max Change=0.05
Calibration Tolerance=0.2
Calibration Maximum=1.5
Calibration Minimum=0.5
Calibration Optimization Method= 1
WQ AD Non Conservative
WQ ULTIMATE=-1
WQ Max Comp Step=1HOUR
WQ Output Interval=15MIN
WQ Output Selected Increments= 0
WQ Output face flow=0
WQ Output face velocity=0
WQ Output face area=0
WQ Output face dispersion=0
WQ Output cell volume=0
WQ Output cell surface area=0
WQ Output cell continuity=0
WQ Output cumulative cell continuity=0
WQ Output face conc=0
WQ Output face dconc_dx=0
WQ Output face courant=0
WQ Output face peclet=0
WQ Output face adv mass=0
WQ Output face disp mass=0
WQ Output cell mass=0
WQ Output cell source sink temp=0
WQ Output nsm pathways=0
WQ Output nsm derived pathways=0
WQ Create Restart=0
WQ Fixed Restart=0
WQ System Summary=0
WQ Write To DSS=0
Sorting and Armoring Iterations= 10
XS Update Threshold= 0.02
Bed Roughness Predictor= 0
Hydraulics Update Threshold= 0.02
Energy Slope Method= 1
Volume Change Method= 1
Sediment Retention Method= 0
Sediment TS Multiplier= 1
Warm Up Method= 0
XS Weighting Method= 0
Number of US Weighted Cross Sections= 1
Number of DS Weighted Cross Sections= 1
Upstream XS Weight=0
Main XS Weight=1
Downstream XS Weight=0
Number of DS XS's Weighted with US Boundary= 1
Upstream Boundary Weight= 1
Weight of XSs Associated with US Boundary= 0
Number of US XS's Weighted with DS Boundary= 1
Downstream Boundary Weight= 0.5
Weight of XSs Associated with DS Boundary= 0.5
Percentile Method= 0
Sediment Output Level= 3
Mass or Volume Output= 0
Output Increment Type= 1
Profile and TS Output Increment= 1
Transport Output Increment 1
XS Output Flag= 0
XS Output Increment= 10
Read HDF5 Sediment Hotstart= 0
Sediment Hotstart Type= 0
Write Gradation File= 0
Read Gradation Hotstart= 0
Write HDF5 File= 1
Write Binary Output= 1
Write DSS Sediment File= 0
DSS Sediment Output Type= 1
SV Curve= 0
Specific Gage Flag= 0
Subcell Erosion Methods= 0
Subcell Deposition Methods= 0
Advection Scheme= 1
Matrix Solver= 0
Implicit Weighting Factor= 1
Maximum Outer Loop Convergence Iterations= 5
Convergence Maximum Absolute= 0.001
Convergence RMSE= 0.0001
Grain Fractions Max Abs Error= 0.001
Max Subgrid Regions= 1
Max Subgrid Length Scale= 3.402823E+38
Initial Layer Thickness= 3.402823E+38
Min Layer Thickness= 3.402823E+38
Max Layer Thickness= 3.402823E+38
Number of Layers= 5

--- RUSHRN.f01 (steady flow) ---

Flow Title=Flow
Program Version=6.10
Number of Profiles= 6
Profile Names=01pct,10pct,04pct,02pct,0_2pct,01plus
River Rch & RM=RUSHRN,Main            ,2529
     541     285     379     457     756     799
Boundary for River Rch & Prof#=RUSHRN,Main            , 1
Up Type= 0
Dn Type= 3
Dn Slope=0.02241
Boundary for River Rch & Prof#=RUSHRN,Main            , 2
Up Type= 0
Dn Type= 3
Dn Slope=0.02241
Boundary for River Rch & Prof#=RUSHRN,Main            , 3
Up Type= 0
Dn Type= 3
Dn Slope=0.02241
Boundary for River Rch & Prof#=RUSHRN,Main            , 4
Up Type= 0
Dn Type= 3
Dn Slope=0.02241
Boundary for River Rch & Prof#=RUSHRN,Main            , 5
Up Type= 0
Dn Type= 3
Dn Slope=0.02241
Boundary for River Rch & Prof#=RUSHRN,Main            , 6
Up Type= 0
Dn Type= 3
Dn Slope=0.02241
DSS Import GetInterval= 0
DSS Import GetPeak= 0
DSS Import FillOption= 0

--- RUSHRN.g01 (geometry) ---

Geom Title=Geometry
Program Version=6.10

River Reach=RUSHRN          ,Main
Reach XY= 30
     2172437.751      403622.394 2172487.8719644403526.409020415
2172535.72562191403490.2986602732172547.80873688403439.334665138
2172502.28057848403392.2737503592172502.11271915403268.827086109
     2172568.859403111.9357870882172526.20659813 402906.09937537
2172634.23341021402830.6366023112172669.72236291402775.453230798
 2172727.5979367402752.9377295452172759.66489734402642.041384035
2172734.85044095402578.1190542192172772.19230698402454.971101372
2172787.03285103402439.1070715272172849.72135606402425.929691897
 2172910.8746324402369.1262301942172918.60628207402302.346722054
2172987.24859111402131.1860313322172998.96712444402066.165566052
 2173095.3286704401987.1793162732173091.80324799 401958.89199834
 2173041.8597638401943.7830451412173029.26896947401926.659564849
     2173099.155      401899.7852173127.11953428401843.957631773
2173163.57077568401812.2512136822173156.66981083401764.900559328
2173062.45558421401712.8643199642173104.04693655 401662.85277896

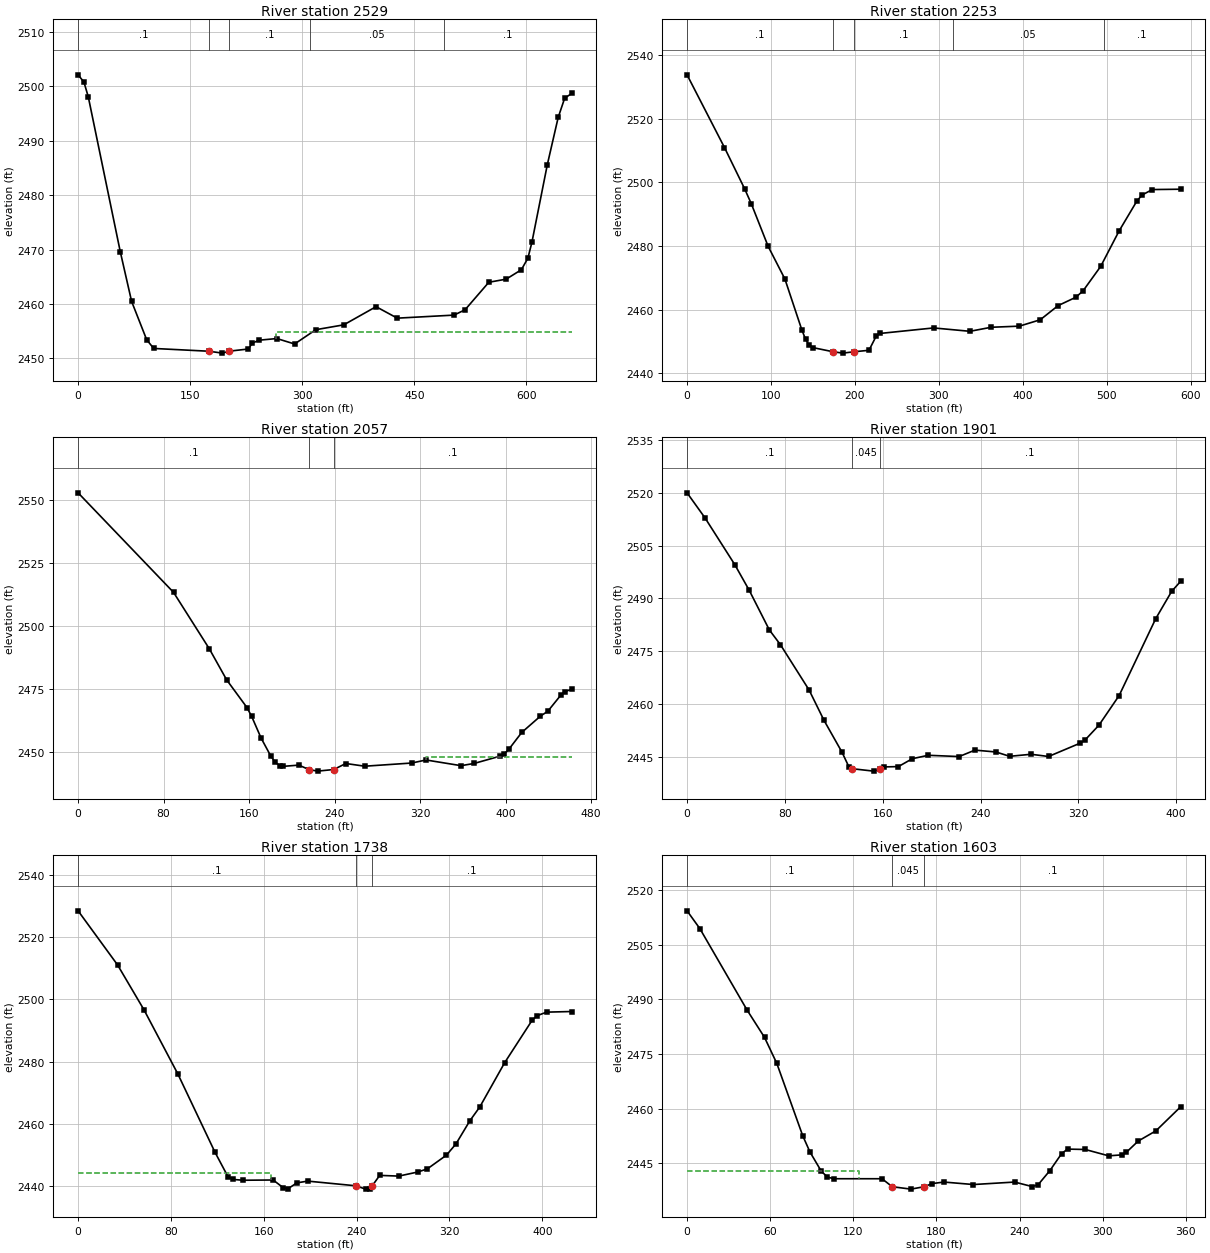
Type RM Length L Ch R = 1 ,2529    ,204.8,276.8,204.8
XS GIS Cut Line= 2
2172604.62030651403719.4607907542172047.16834671403365.061340959
#Sta/Elev= 30
       0 2502.12     7.8 2500.79    13.6 2498.09    56.4 2469.62    71.6 2460.46
    91.8  2453.4   101.2 2451.81  174.83  2451.3   193.2 2450.95   202.2 2451.31
     228 2451.71   232.8 2452.77   242.3 2453.33     266 2453.63   289.7 2452.63
   318.1 2455.26   355.5 2456.15   398.7 2459.49   427.1 2457.38     503 2457.94
   517.8 2458.92   549.6 2463.98   572.8 2464.55   593.1 2466.28   601.8 2468.38
   607.2  2471.3   627.9 2485.62   642.4 2494.28   651.1 2497.83   660.6  2498.7
#Mann= 5 ,-1,0
       0      .1       0  174.83    .045       0   202.2      .1       0
     310     .05       0     490      .1       0
#XS Ineff= 2 , 0
                           265.2          2454.8
Permanent Ineff=
       F       F
Bank Sta=174.83,202.2
XS Rating Curve= 0 ,0
Exp/Cntr=0.3,0.1

Type RM Length L Ch R = 1 ,2253    ,180.6,195.3,210.6
XS GIS Cut Line= 5
2172684.75204097403379.4300371872172550.36736542403378.688195011
2172431.22210436403436.2241544122172231.53619967403371.876246954
2172146.67320871403299.108034841
#Sta/Elev= 30
       0 2533.83    44.6 2510.97    68.6 2498.01    76.6 2493.28    96.6 2479.93
   116.6 2469.64   136.8 2453.63   141.3 2450.65   145.7 2448.79   150.1 2448.07
   173.8 2446.78   185.7 2446.34     199 2446.77   216.8 2447.23   225.7 2451.85
   230.1 2452.53   293.8 2454.26   337.1  2453.2   362.4 2454.47     396 2454.82
   420.9 2456.83   442.2 2461.28   463.2 2463.89   471.8 2465.88   492.9  2473.6
   514.8 2484.73   535.9 2494.09   542.1 2496.03   554.4 2497.76   588.3 2497.87
#Mann= 5 ,-1,0
       0      .1       0   173.8    .045       0     199      .1       0
   316.7     .05       0  496.49      .1       0
Bank Sta=173.8,199
XS Rating Curve= 0 ,0
Exp/Cntr(USF)=0,0
Exp/Cntr=0.3,0.1

Type RM Length L Ch R = 1 ,2057    ,165,156.6,145.3
XS GIS Cut Line= 4
2172744.65601428403277.7843227692172636.81117059 403263.08364668
2172436.31378219403170.4385720452172306.07457015403193.211040957
#Sta/Elev= 30
       0 2552.86    89.3 2513.42   122.8 2491.04     139 2478.75     158 2467.78
   162.4 2464.26   171.2  2455.7   180.1 2448.71   184.5 2446.04   188.9 2444.76
   192.1 2444.49   206.5 2444.97   216.2 2443.19   224.1 2442.59  239.19 2443.23
   250.5 2445.61   268.2 2444.54   312.2  2445.8   325.5 2447.01   358.3 2444.75
   370.5 2445.63   394.8 2448.52   398.9 2449.48   402.9 2451.18   415.1 2457.92
   432.4 2464.32   439.5 2466.33   451.7 2472.72   455.7 2474.09   461.9 2475.09
#Mann= 3 ,-1,0
       0      .1       0   216.2    .045       0  239.19      .1       0
#XS Ineff= 2 , 0
                          325.24         2448.16
Permanent Ineff=
       F       F
Bank Sta=216.2,239.19
XS Rating Curve= 0 ,0
Exp/Cntr=0.3,0.1

Type RM Length L Ch R = 1 ,1901    ,157.4,162.3,166.2
XS GIS Cut Line= 5
2172706.73662391403060.4311273372172646.45246424403051.500140719
2172510.25491831403074.9439805922172471.18185186402975.586754464
2172376.29011904402952.142914592
#Sta/Elev= 30
       0 2520.03    14.7  2512.9      39 2499.64    50.9 2492.29    67.3 2481.06
    76.4 2476.85    99.8 2463.99     112 2455.36   126.7 2446.32   132.3 2442.19
   135.2 2441.62   152.5 2440.94  157.54 2441.57   161.3 2442.14   172.8 2442.23
   184.2 2444.47   197.2 2445.44   222.5 2445.08   235.4 2446.91   252.6 2446.38
   263.8 2445.15   281.3 2445.73   295.6  2445.1   321.4 2448.88   325.5  2449.8
   336.8 2453.99   353.3  2462.4   383.3  2484.3   396.3 2492.04   403.7 2494.91
#Mann= 3 ,-1,0
       0      .1       0   135.2    .045       0  157.54      .1       0
Bank Sta=135.2,157.54
XS Rating Curve= 0 ,0
Exp/Cntr(USF)=0,0
Exp/Cntr=0.3,0.1

Type RM Length L Ch R = 1 ,1738    ,126.9,135.5,139.1
XS GIS Cut Line= 3
2172755.56295083402995.8921411472172574.67361116402921.327069835
2172350.97839723402868.855352986
#Sta/Elev= 30
       0 2528.35      34    2511    56.8 2496.58    85.9 2476.06     118 2450.87
   129.1 2443.09   133.5 2442.18   142.1 2441.92   168.1    2442   176.7 2439.53
   181.1 2439.25   188.5 2441.08   197.9 2441.64   239.3 2440.14   247.8 2439.07
   251.6 2439.18  253.49 2440.16   259.9 2443.48   276.3 2443.25   292.7 2444.56
     301 2445.58   317.4 2449.97   325.6 2453.57   337.6 2461.01   346.1 2465.41
   367.6 2479.65   391.3 2493.28   395.4 2494.69   403.7 2495.85   425.4 2496.05
#Mann= 3 ,0,0
       0      .1       0   239.3    .045       0  253.49      .1       0
#XS Ineff= 2 , 0
          165.83 2444.16
Permanent Ineff=
       F       F
Bank Sta=239.3,253.49
XS Rating Curve= 0 ,0
Exp/Cntr(USF)=0,0
Exp/Cntr=0.3,0.1

Type RM Length L Ch R = 1 ,1603    ,140,136.4,133.2
XS GIS Cut Line= 4
2172766.96673224402917.2450643042172656.36387731402862.381828827
2172625.74369275402825.9887491882172451.29658776402763.605633446
#Sta/Elev= 30
       0 2514.25     9.2  2509.4    43.3 2487.05    55.9 2479.55    64.8 2472.39
    83.5 2452.55    88.7 2448.12    96.9 2442.83   101.3 2441.25   105.8 2440.78
   140.7 2440.78  148.08 2438.59   161.6 2437.93     1712438.583   176.9 2439.45
   185.4 2439.87   206.7 2439.19   236.4 2439.87   249.2 2438.62   253.4 2439.15
   261.9 2443.03   270.4  2447.7   274.6 2448.91   287.4  2448.8   304.3 2447.06
   313.7 2447.32   317.1 2448.04   325.6 2451.11   338.4 2453.92   356.3 2460.53
#Mann= 3 ,-1,0
       0      .1       0  148.08    .045       0     171      .1       0
#XS Ineff= 2 , 0
           124.3  2442.8
Permanent Ineff=
       F       F
Bank Sta=148.08,171
XS Rating Curve= 0 ,0
Exp/Cntr(USF)=0,0
Exp/Cntr=0.3,0.1

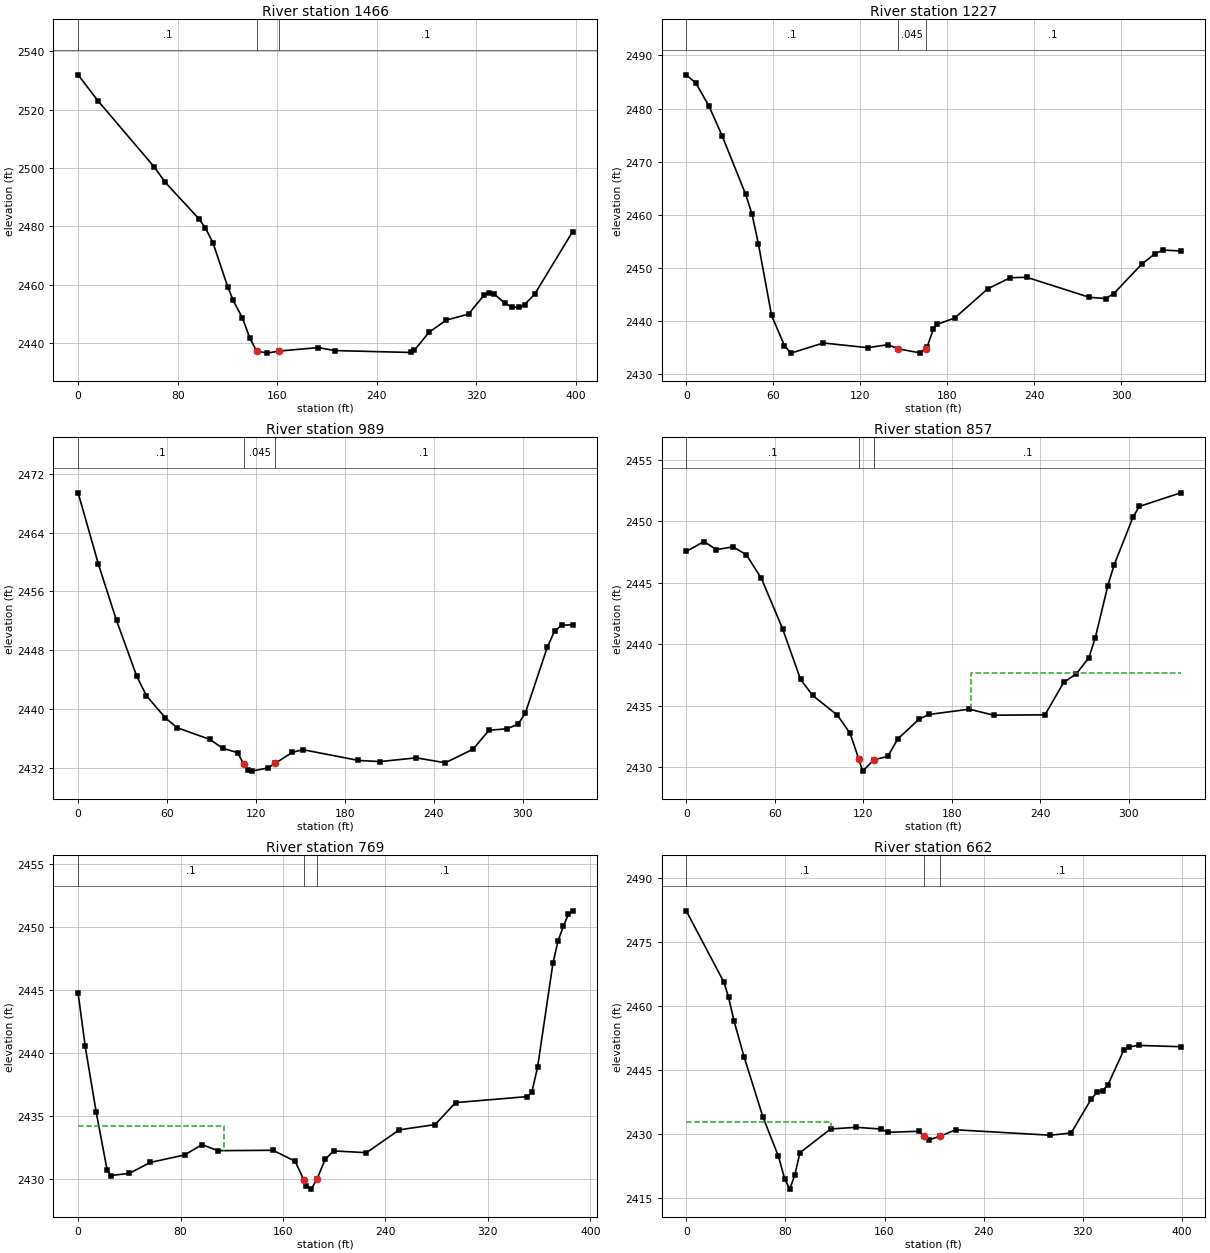
Type RM Length L Ch R = 1 ,1466    ,236.6,239.8,235.4
XS GIS Cut Line= 4
2172862.14489647402821.8421167572172719.48454577402745.710015329
2172607.49420567402661.1116533322172514.44918104402641.280209621
#Sta/Elev= 30
       0 2531.89    15.8 2523.05    61.2 2500.31    69.9 2495.12    97.4 2482.41
     102  2479.6   108.4 2474.28   120.1 2459.38   124.6 2454.62     132 2448.58
   137.9 2441.78   143.3 2437.35   151.9 2436.59   161.22437.294     193 2438.48
     206 2437.47   267.3 2436.81   270.1 2437.59     282 2443.78   295.8 2447.92
   313.6 2449.94   325.9 2456.38     330 2457.33   334.1 2456.87   342.8 2453.68
   348.6 2452.33   354.5 2452.22   358.6 2453.18   366.8 2456.82   397.2 2478.18
#Mann= 3 ,-1,0
       0      .1       0   143.3    .045       0   161.2      .1       0
Bank Sta=143.3,161.2
XS Rating Curve= 0 ,0
Exp/Cntr=0.3,0.1

Type RM Length L Ch R = 1 ,1227    ,228.2,237.3,238.5
XS GIS Cut Line= 3
2172888.81349493402596.1405088372172728.77908155402516.775219972
 2172614.0273988402402.133239962
#Sta/Elev= 30
       0 2486.34     6.7 2484.77    15.7 2480.43    24.7  2474.9    40.9  2463.9
    45.4 2460.09    49.8 2454.46    58.8 2441.12    67.7 2435.41    72.2 2434.01
    94.5 2435.92   125.1 2435.03   139.1  2435.6     146 2434.82   160.9 2434.07
     1652434.842   165.9 2435.08   170.4 2438.55   172.8  2439.4   185.1 2440.62
   207.8  2446.1   223.3 2448.19   234.7 2448.27   277.8 2444.51   289.1 2444.27
   294.7 2445.21   313.9 2450.73     323 2452.69   328.7 2453.39   340.8 2453.22
#Mann= 3 ,-1,0
       0      .1       0     146    .045       0     165      .1       0
Bank Sta=146,165
XS Rating Curve= 0 ,0
Exp/Cntr(USF)=0,0
Exp/Cntr=0.3,0.1

Type RM Length L Ch R = 1 ,989     ,139.5,132.4,123.5
XS GIS Cut Line= 3
2172976.62915482402473.5296641242172896.36589113402371.816735136
2172730.30396625402253.497613661
#Sta/Elev= 30
       0 2469.44    13.6 2459.76    25.9 2452.04    39.5 2444.46    46.1 2441.77
    58.8 2438.78    66.7 2437.43    88.9 2435.83    97.6 2434.61   107.5 2434.04
   111.6 2432.52   114.5 2431.71     117 2431.51   127.8 2431.93     133 2432.58
   144.5 2434.08   151.7 2434.43     189 2432.97   203.5 2432.81     228 2433.32
   247.7 2432.65   266.4 2434.51   277.1 2437.08   289.3 2437.28   296.8 2437.92
   301.7 2439.46   316.4 2448.37   321.3 2450.59   326.3  2451.4   333.5 2451.45
#Mann= 3 ,0,0
       0      .1       0   111.6    .045       0     133      .1       0
Bank Sta=111.6,133
XS Rating Curve= 0 ,0
Exp/Cntr(USF)=0,0
Exp/Cntr=0.3,0.1

Type RM Length L Ch R = 1 ,857     ,88,88.3,88.5
XS GIS Cut Line= 3
2173060.02030144402287.7743749342172970.70865437402268.758945977
2172741.75460429402184.651781969
#Sta/Elev= 30
       0 2447.54    12.1 2448.35    20.3 2447.69    31.7 2447.91    40.7 2447.28
    50.9 2445.36    65.3 2441.26    77.5 2437.13    85.7 2435.83   102.5 2434.22
   111.1 2432.74  117.01 2430.64   119.6 2429.67   127.2 2430.59   136.6 2430.87
   143.4 2432.29   157.9  2433.9   164.6 2434.28     192 2434.71   208.3 2434.22
   243.2 2434.25   255.9 2436.89   264.5 2437.59     273 2438.91   277.3 2440.52
   285.8 2444.75     290 2446.42   302.8 2450.31   307.1  2451.2   335.2 2452.31
#Mann= 3 ,0,0
       0      .1       0  117.01    .045       0   127.2      .1       0
#XS Ineff= 2 , 0
                          192.85         2437.63
Permanent Ineff=
       F       F
Bank Sta=117.01,127.2
XS Rating Curve= 0 ,0
Exp/Cntr(USF)=0,0
Exp/Cntr=0.3,0.1

Type RM Length L Ch R = 1 ,769     ,106.8,106.9,105.9
XS GIS Cut Line= 4
 2173133.2451385402241.5396260852172975.56001434402177.613813696
2172907.95017411402150.5648673542172764.97672916402158.460158791
#Sta/Elev= 30
       0 2444.74     5.5 2440.56    14.1 2435.32    22.7 2430.71    25.7  2430.3
      40 2430.47    56.4 2431.34    83.2 2431.93    96.8 2432.75   109.1 2432.27
   152.2  2432.3   169.5 2431.43   176.2 2429.97   178.1 2429.44   182.1 2429.22
   186.7 2430.05   192.9 2431.58   199.6 2432.25   225.2 2432.11   250.8 2433.92
   278.8 2434.34   294.8 2436.08   350.9 2436.56   354.4 2436.93   358.9 2438.92
   370.9 2447.17   374.9 2448.92     379 2450.07     383 2451.04   386.2 2451.29
#Mann= 3 ,-1,0
       0      .1       0   176.2    .045       0   186.7      .1       0
#XS Ineff= 2 , 0
           113.9 2434.25
Permanent Ineff=
       F       F
Bank Sta=176.2,186.7
XS Rating Curve= 0 ,0
Exp/Cntr(USF)=0,0
Exp/Cntr=0.3,0.1

Type RM Length L Ch R = 1 ,662     ,178.6,242.1,239.4
XS GIS Cut Line= 4
2173190.61183906402110.1500464562173136.93743435402114.183689222
2173049.68073211402092.135860156  2172808.725085402008.595363594
#Sta/Elev= 30
       0 2482.28    30.5  2465.5    34.1 2462.09    38.5 2456.54    46.6 2448.15
    61.9 2433.97    74.3 2424.83    79.4 2419.51    83.5 2417.09    87.6 2420.41
    91.7 2425.61   116.5 2431.18   137.1 2431.57   156.8 2431.17   163.1 2430.39
   187.8 2430.65   191.92429.469   196.2 2428.67   204.6 2429.47   217.4 2430.99
   293.6 2429.72   310.5 2430.23   326.5 2438.09   331.7 2439.87     336 2440.18
   340.2 2441.53   352.9  2449.6   357.1 2450.43   365.6 2450.75   398.9 2450.45
#Mann= 3 ,-1,0
       0      .1       0   191.9    .045       0   204.6      .1       0
#XS Ineff= 2 , 0
          117.07 2432.77
Permanent Ineff=
       F       F
Bank Sta=191.9,204.6
XS Rating Curve= 0 ,0
Exp/Cntr(USF)=0,0
Exp/Cntr=0.3,0.1

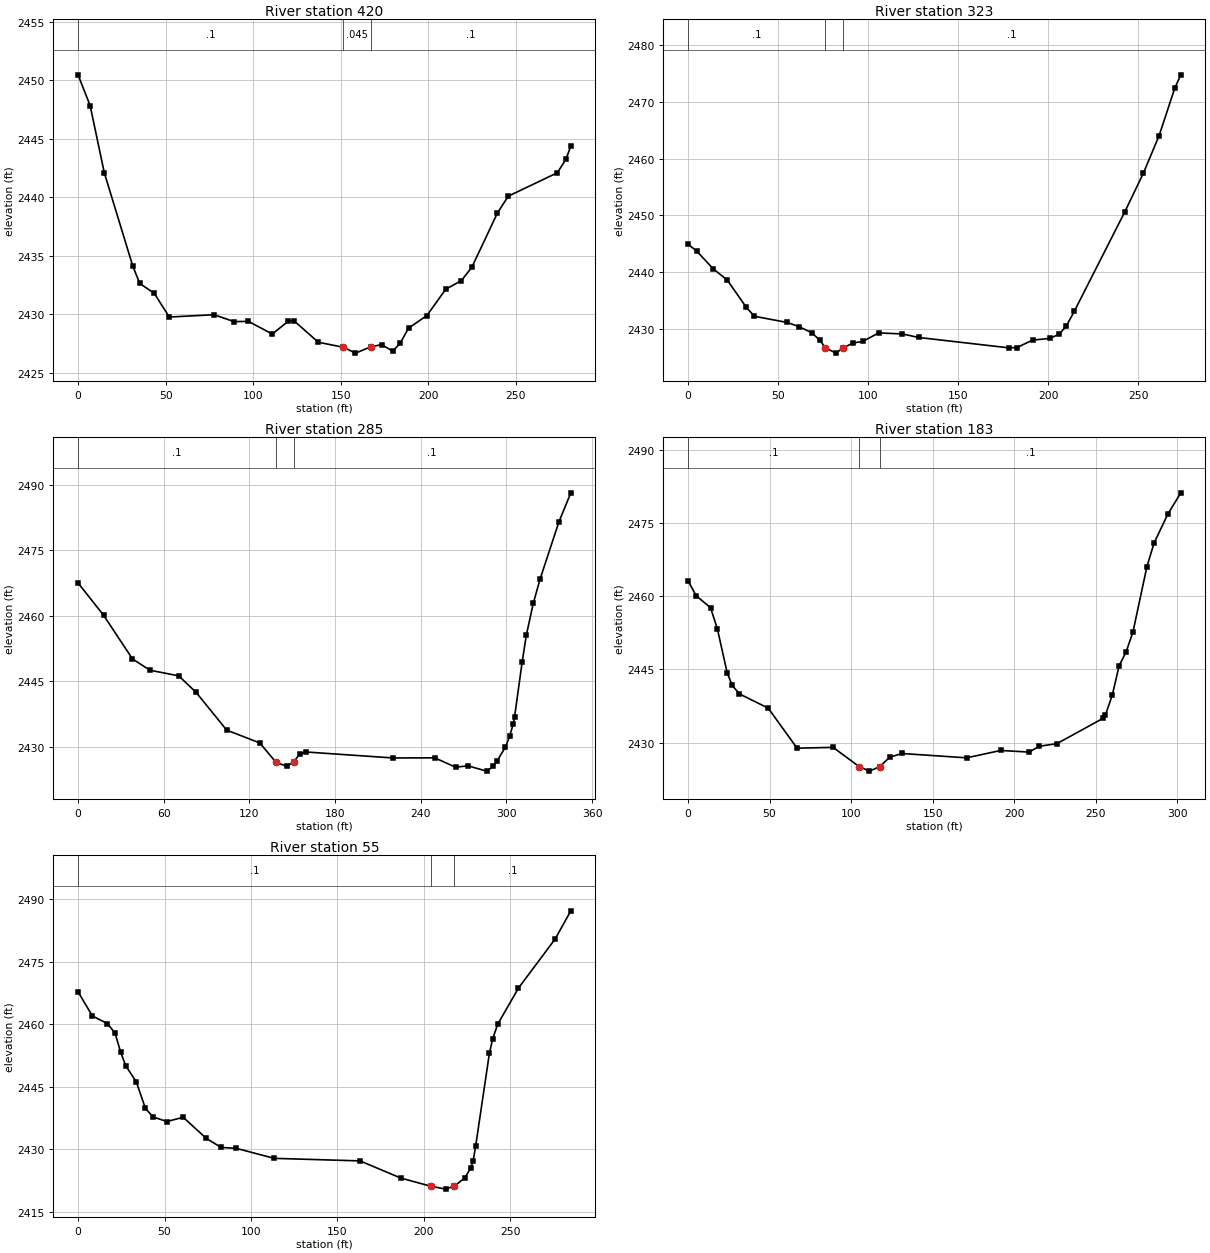
Type RM Length L Ch R = 1 ,420     ,152.2,97,97.9
XS GIS Cut Line= 6
2173178.97234423401960.030552268 2173147.5936571401965.153603228
2173141.27094912401965.3762934152173002.02194918 401914.78724713
2172976.21447146 401886.112271882172929.86399129401853.727244843
#Sta/Elev= 30
       0 2450.46     6.9 2447.83      15 2442.09    31.2 2434.16    35.2 2432.65
    43.5 2431.81    52.1 2429.78    77.6 2429.98    89.1 2429.39    97.3 2429.41
   110.9 2428.33   120.1 2429.43   123.4 2429.45   137.2 2427.63   151.5  2427.2
   158.4  2426.7   167.1 2427.23   173.4 2427.43   179.7 2426.86     184 2427.56
   188.7 2428.83   199.2 2429.91     210 2432.16   218.9 2432.89   224.9 2434.04
   239.5 2438.67   245.7  2440.1   273.7  2442.1   278.6 2443.25281.3962 2444.39
#Mann= 3 ,0,0
       0      .1       0   151.5    .045       0   167.1      .1       0
Bank Sta=151.5,167.1
XS Rating Curve= 0 ,0
Exp/Cntr(USF)=0,0
Exp/Cntr=0.3,0.1

Type RM Length L Ch R = 1 ,323     ,36.7,37.3,37.7
XS GIS Cut Line= 4
2173181.44798831401918.589758395 2173147.5936571401902.396228966
2172979.58072856401810.8658484962172941.90128542401786.919037503
#Sta/Elev= 30
       0 2444.95       5 2443.66      14 2440.59    21.8 2438.61    32.4 2433.79
    36.9 2432.23    55.1 2431.14    61.6 2430.41    68.8 2429.31    73.3 2427.97
    76.3 2426.65    82.2 2425.74   85.83 2426.62    91.5 2427.52      97  2427.8
   105.8  2429.3   118.9 2429.12     128  2428.5   178.1 2426.67   182.5 2426.72
   191.3 2428.04   200.8 2428.33   206.1  2429.1     210 2430.53   214.5 2433.17
   242.4 2450.61   252.8 2457.48   261.5 2464.08   270.2 2472.45   273.5 2474.77
#Mann= 3 ,0,0
       0      .1       0    76.3    .045       0   85.83      .1       0
Bank Sta=76.3,85.83
XS Rating Curve= 0 ,0
Exp/Cntr(USF)=0,0
Exp/Cntr=0.3,0.1

Type RM Length L Ch R = 1 ,285     ,117.7,102.3,89.7
XS GIS Cut Line= 3
2173261.87359338401888.0830191732173166.73408573401873.370225936
2172953.71272366401744.855944696
#Sta/Elev= 30
       0 2467.53    17.9 2460.13    38.1 2450.16    50.3 2447.57    70.5 2446.28
    82.7 2442.49   104.1 2433.87   127.3 2430.93   138.6 2426.51     146 2425.62
  150.88 2426.51   155.3 2428.45   159.5 2428.87   220.7  2427.5   249.8 2427.53
   264.4 2425.39   273.1  2425.7   286.1 2424.49   290.8 2425.58   293.5 2426.87
   299.3 2429.97   302.2 2432.45   304.8 2435.33   305.7 2436.89     311 2449.41
   313.9 2455.53   318.8 2462.87   323.5 2468.34   336.7 2481.45   345.1 2488.14
#Mann= 3 ,0,0
       0      .1       0   138.6    .045       0  150.88      .1       0
Bank Sta=138.6,150.88
XS Rating Curve= 0 ,0
Exp/Cntr(USF)=0,0
Exp/Cntr=0.3,0.1

Type RM Length L Ch R = 1 ,183     ,105.2,128,139.2
XS GIS Cut Line= 4
2173256.67993616401788.5735685032173176.13101495 401750.65283884
2173138.36226024401783.0927738062172984.60915242401727.778400776
#Sta/Elev= 30
       0 2463.14       5 2460.06    13.8 2457.62      18  2453.3      24 2444.33
    27.1  2441.7    31.5 2439.97    49.2 2437.04    66.9 2428.85      89 2429.01
     105 2425.07   111.3 2424.15  117.67 2425.09   123.6 2426.97   131.2 2427.76
   170.9 2426.87   191.7 2428.38   209.2 2428.05   215.4 2429.24   226.2 2429.77
   254.6 2434.97   255.9 2435.54   260.2 2439.73   264.4 2445.73   268.7 2448.58
   272.9 2452.68   281.4 2465.97   285.8 2470.84   294.2 2476.74   302.2 2481.13
#Mann= 3 ,0,0
       0      .1       0     105    .045       0  117.67      .1       0
Bank Sta=105,117.67
XS Rating Curve= 0 ,0
Exp/Cntr(USF)=0,0
Exp/Cntr=0.3,0.1

Type RM Length L Ch R = 1 ,55      ,,,
XS GIS Cut Line= 4
2173263.71010347401782.1384803512173160.14750443401735.880519445
2173109.67980741401725.5242595412173008.52462109401660.844823091
#Sta/Elev= 30
       0 2467.77     8.3 2461.98      17 2460.15    21.4 2457.87    24.6 2453.34
    27.6 2450.03    33.7 2446.16    38.9 2439.88    43.3 2437.78    51.4 2436.67
    60.8 2437.69      74 2432.68    82.7 2430.46    91.5 2430.24   113.4 2427.84
   163.1 2427.23   186.6 2423.12   203.9 2421.17   212.6 2420.46   217.6 2421.18
   223.7 2423.16   227.1 2425.55   228.5 2427.26     230 2430.91   237.9 2453.03
   239.8  2456.5   242.7 2459.99   254.7 2468.66   275.9 2480.42     285 2487.19
#Mann= 3 ,0,0
       0      .1       0   203.9    .045       0   217.6      .1       0
Bank Sta=203.9,217.6
XS Rating Curve= 0 ,0
Exp/Cntr(USF)=0,0
Exp/Cntr=0.3,0.1
LCMann Table=0

Chan Stop Cuts=-1
Use User Specified Reach Order=0
Composite Channel Slope=5